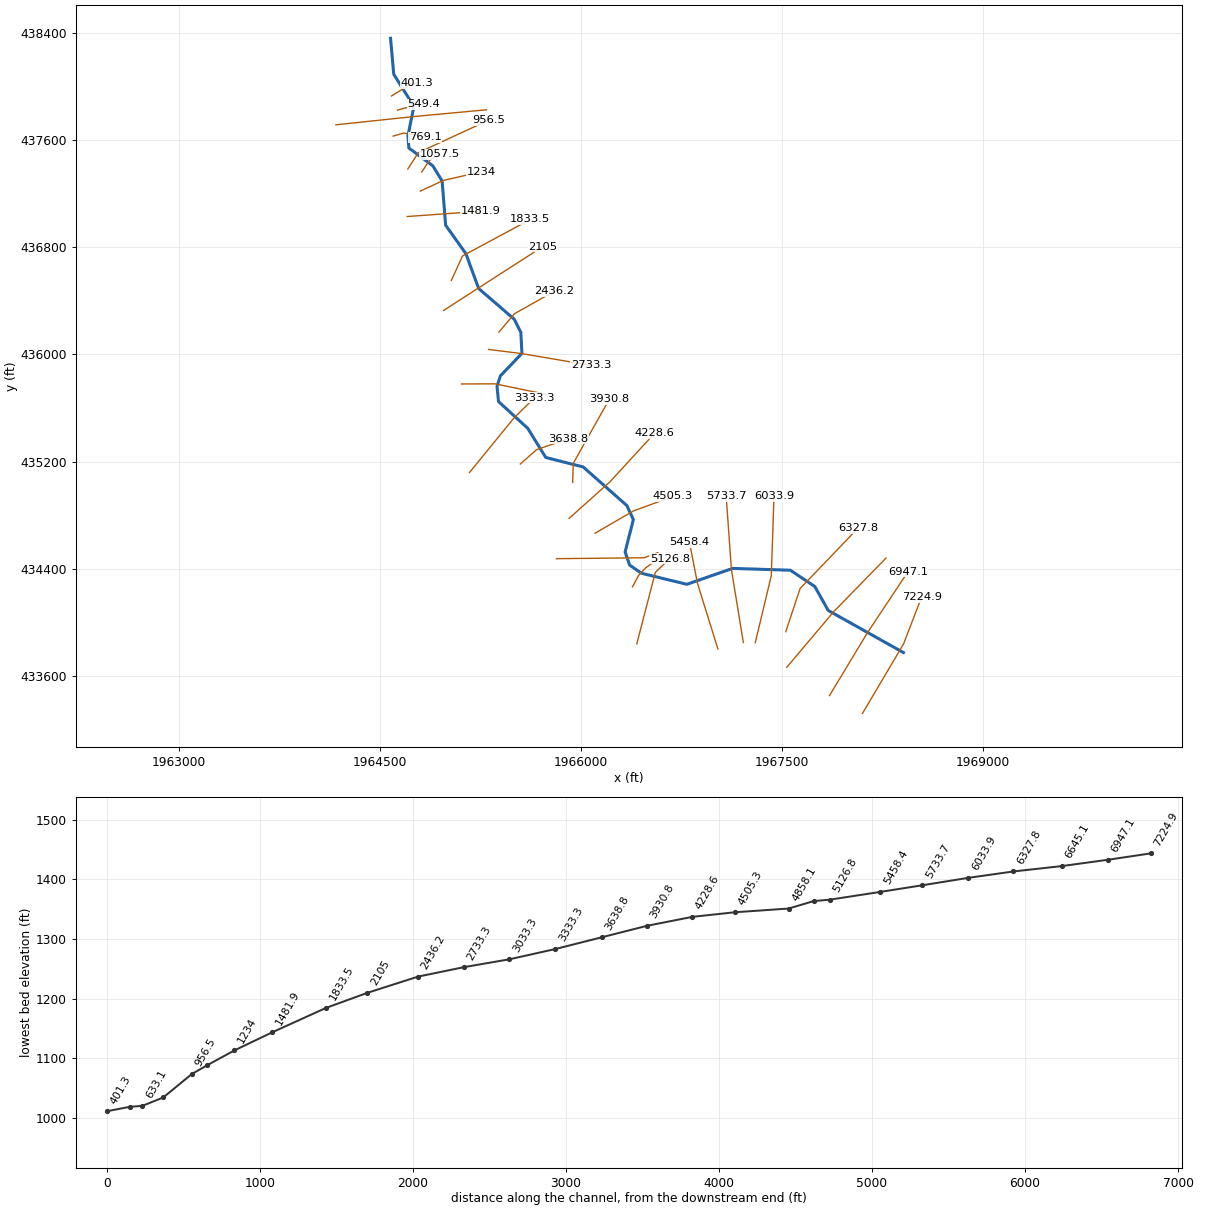
--- RamseyBrh.prj (project) ---

Proj Title=RamseyBrh
Current Plan=p01
Default Exp/Contr=0,0
English Units
Geom File=g01
Flow File=f01
Plan File=p01
BEGIN DESCRIPTION:
END DESCRIPTION:
DSS Export Rating Curves= 0
DSS Export Rating Curve Sorted= 0
DSS Export Volume Flow Curves= 0
DXF OffsetX= 0
DXF OffsetY= 0
DXF ScaleX= 0
DXF ScaleY= 0

--- RamseyBrh.p01 (plan) ---

Plan Title=Floodplain
Program Version=4.00
Geom File=g01
Flow File=f01
K Sum by GR=0
Std Step Tol=0.01
Critical Tol=0.01
Num of Std Step Trials=20
Max Error Tol=0.3
Flow Tol Ratio=0.001
Split Flow NTrial=30
Split Flow Tol=0.02
Split Flow Ratio=0.02
Log Output Level=0
Friction Slope Method=1
Unsteady Friction Slope Method=2
Unsteady Bridges Friction Slope Method=1
Global Log Level=0
CheckData=False
Run HTab=0
Run UNet=0
Run PostProcess=0
UNET Theta=0
UNET Theta Warmup=0
UNET ZTol=0
UNET ZSATol=0
UNET MxIter=0
UNET MaxInSteps=0
UNET DtIC=0
UNET DtMin=0
UNET MaxCRTS=0
UNET WFStab=0
UNET SFStab=0
UNET WFX=0
UNET SFX=0
UNET DSS MLevel=0
UNET DZMax Abort=0
UNET Convert EG Bridges=0
UNET Use Existing IB Tables=0
UNET Froude Limit=0
UNET Froude Power=0
Write IC File=0
Echo Input=False
Echo Output=False
Write Detailed=0

--- RamseyBrh.f01 (steady flow) ---

Flow Title=NFF Regression Equation
Program Version=4.00
Number of Profiles=1
Profile Names=P100yr
River Rch & RM=RamseyBrh,Main      ,7224.9
415.2188
River Rch & RM=RamseyBrh,Main      ,6947.1
415.2188
River Rch & RM=RamseyBrh,Main      ,6645.1
540.0851
River Rch & RM=RamseyBrh,Main      ,6327.8
542.6412
River Rch & RM=RamseyBrh,Main      ,5022.9
601.7766
River Rch & RM=RamseyBrh,Main      ,3333.3
645.7522
River Rch & RM=RamseyBrh,Main      ,1833.5
701.5918
River Rch & RM=RamseyBrh,Main      ,1481.9
786.9765
Boundary for River Rch & Prof#=RamseyBrh,Main      ,1
Up Type=0
Dn Type=3
Dn Slope=0.057646

--- RamseyBrh.g01 (geometry) ---

Geom Title=USGS 3m DEM
Program Version=4.10

River Reach=RamseyBrh       ,Main
Reach XY= 30
     1968406.926       433775.05     1967845.648      434089.292
     1967745.467      434268.105     1967563.176      434389.633
     1967131.536      434403.199     1966790.364      434284.446
     1966452.064      434367.064     1966363.523      434427.827
      1966329.92      434526.043     1966391.366      434767.606
      1966342.69      434872.272       1966016.3      435160.466
      1965737.61      435231.036     1965603.106      435448.661
     1965385.013      435648.314      1965373.94      435762.897
     1965399.082       435840.11     1965559.581      436007.835
     1965551.691      436164.873     1965502.412      436262.897
     1965236.787      436492.064     1965141.301       436752.48
     1964990.259      436964.286     1964964.217      437294.147
     1964894.779      437407.768     1964715.953      437540.675
     1964709.009      437630.953     1964753.572      437850.969
     1964603.106      438091.022     1964579.243      438359.099

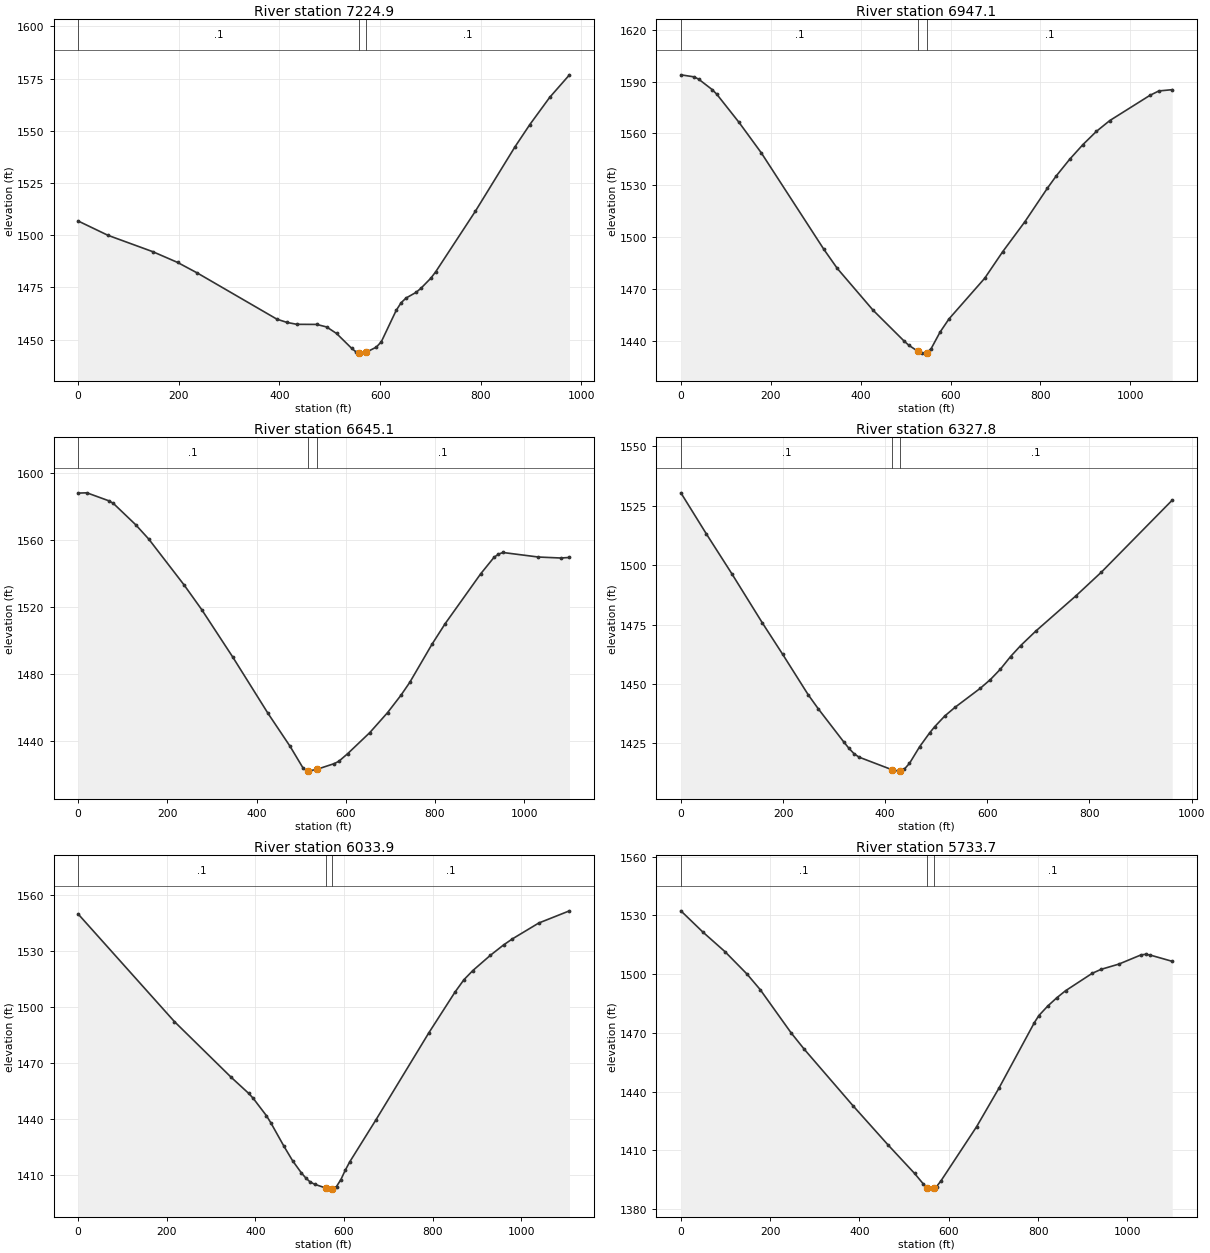
Type RM Length L Ch R = 1 ,7224.9  ,278,277.7,276.5
XS GIS Cut Line= 3
      1968101.54      433321.237     1968408.036      433839.841
     1968542.314      434188.701
#Sta/Elev= 30
       0 1506.81    59.2 1499.96   148.1 1492.14   197.5 1486.98     237 1481.89
     395 1459.81   414.8 1458.27   434.5 1457.35     474  1457.3   493.8 1456.08
   513.5 1452.96   543.2 1445.92     553 1443.98   557.1 1443.81   562.9 1443.56
   572.8 1444.03   592.5 1446.43   602.4 1449.01   631.9    1464   641.8  1467.7
   651.6 1469.94   671.3 1472.62   681.1 1474.59   700.8 1479.44   710.6 1482.55
   789.3  1511.5     868 1542.33   897.5 1552.98   936.9 1565.97   976.2 1576.76
#Mann= 3 , 0 , 0
       0      .1       0   557.1    .045       0   572.8      .1       0
Bank Sta=557.1,572.8
XS Rating Curve= 0 ,0
Exp/Cntr=0.3,0.1

Type RM Length L Ch R = 1 ,6947.1  ,305.6,301.9,298.2
XS GIS Cut Line= 3
     1967855.255       433454.32     1968137.888      433922.578
     1968440.413      434377.715
#Sta/Elev= 30
       0 1593.95    29.8 1592.75    39.8 1591.39    69.6 1585.42    79.6 1582.82
   129.3 1566.47     179 1548.79   318.2 1492.97   348.1 1481.91   427.6 1457.77
   497.2 1439.78   507.2 1437.47     527 1434.04     537 1432.91   546.9 1433.12
   556.9  1435.5   576.8  1445.1   596.6  1452.7   676.1 1476.24   715.9 1491.52
   765.6 1508.99   815.2 1528.21   835.1 1535.38   864.9    1545   894.7 1553.59
   924.5 1561.19   954.3 1567.46  1043.8 1582.08  1063.6 1584.62  1093.4 1585.36
#Mann= 3 , 0 , 0
       0      .1       0     527    .045       0   546.9      .1       0
Bank Sta=527,546.9
XS Rating Curve= 0 ,0
Exp/Cntr=0.3,0.1

Type RM Length L Ch R = 1 ,6645.1  ,318.8,317.2,316.6
XS GIS Cut Line= 3
     1967536.154       433665.25     1967887.427       434081.14
     1968276.352      434479.829
#Sta/Elev= 30
       0 1587.89    19.8 1588.04    69.3 1583.25    79.2 1581.69   128.7 1569.14
   158.4 1560.49   237.6 1533.17   277.1 1518.48   346.4 1490.35   425.6 1456.74
   475.1  1437.1   504.8  1423.9   514.7 1422.32   534.5 1423.32   574.2  1426.8
   584.2 1428.14   604.1 1432.69   653.8 1445.25   693.6 1457.15   723.4 1467.41
   743.3 1475.13     793 1497.77   822.9 1510.19   902.4 1539.82   932.3 1549.63
   942.2 1551.51   952.2 1552.51  1031.7 1549.81  1081.5 1549.23  1101.4 1549.54
#Mann= 3 , 0 , 0
       0      .1       0   514.7    .045       0   534.5      .1       0
Bank Sta=514.7,534.5
XS Rating Curve= 0 ,0
Exp/Cntr=0.3,0.1

Type RM Length L Ch R = 1 ,6327.8  ,277.2,293.8,310.3
XS GIS Cut Line= 3
     1967528.942      433931.168     1967635.613      434252.704
     1968067.022      434702.556
#Sta/Elev= 30
       0 1530.46    49.8  1513.2    99.6 1496.45   159.4 1475.73   199.3 1462.46
   249.1 1445.49     269 1439.51   318.8 1425.59   328.8 1422.94   338.8 1420.65
   348.7 1419.16   414.3 1413.77   427.8 1413.26   429.3 1413.39   437.7 1414.15
   447.6 1416.54   467.4 1423.53   487.2 1429.42   497.1 1432.01   516.8 1436.51
   536.6 1440.11   586.1 1448.13   605.9 1451.81   625.7 1456.23   645.5 1461.52
   665.2 1466.12   694.9 1472.24   774.1 1487.21   823.5  1497.1     962 1527.38
#Mann= 3 , 0 , 0
       0      .1       0   414.3    .045       0   429.3      .1       0
Bank Sta=414.3,429.3
XS Rating Curve= 0 ,0
Exp/Cntr=0.3,0.1

Type RM Length L Ch R = 1 ,6033.9  ,296,300,302.4
XS GIS Cut Line= 3
      1967301.09      433849.181     1967420.747      434348.707
     1967440.912      434943.547
#Sta/Elev= 30
       0 1549.67   217.3 1492.16   345.7 1462.31   385.2 1453.72   395.1 1451.15
   424.8  1441.9   434.6 1438.17   464.3  1425.6     484 1417.78   503.8 1411.29
   513.7 1408.58   523.6 1406.43   533.5 1405.22   558.7  1403.2   573.2  1402.6
   573.7 1402.67   583.1    1404     593 1407.73   602.9 1412.72   612.8 1417.12
   672.4 1439.76   791.4 1486.13   850.9 1508.06   870.8 1514.58   890.6  1519.4
   930.3 1527.58     960  1533.1   979.9 1536.34  1039.4 1544.82  1108.8 1551.35
#Mann= 3 , 0 , 0
       0      .1       0   558.7    .045       0   573.7      .1       0
Bank Sta=558.7,573.7
XS Rating Curve= 0 ,0
Exp/Cntr=0.3,0.1

Type RM Length L Ch R = 1 ,5733.7  ,272.9,275.2,277.9
XS GIS Cut Line= 3
     1967212.207      433850.011     1967123.079      434395.664
     1967084.117      434941.739
#Sta/Elev= 30
       0 1532.33    49.4 1521.46    98.7 1511.49   148.1 1500.03   177.7 1492.07
   246.8 1470.02   276.4  1461.6     385 1432.88     464 1412.74   523.3  1398.2
     543 1392.79   551.6 1390.97   562.8 1390.16   566.6 1390.67   572.8  1391.5
   582.8  1394.5   662.4  1422.1   712.2  1441.7   791.8 1475.28   801.7 1478.83
   821.6 1483.69   841.6 1487.86   861.4  1491.5   921.2 1500.41   941.1 1502.44
   980.9 1505.12  1030.7 1509.83  1040.6 1510.11  1050.6 1509.76  1100.4 1506.53
#Mann= 3 , 0 , 0
       0      .1       0   551.6    .045       0   566.6      .1       0
Bank Sta=551.6,566.6
XS Rating Curve= 0 ,0
Exp/Cntr=0.3,0.1

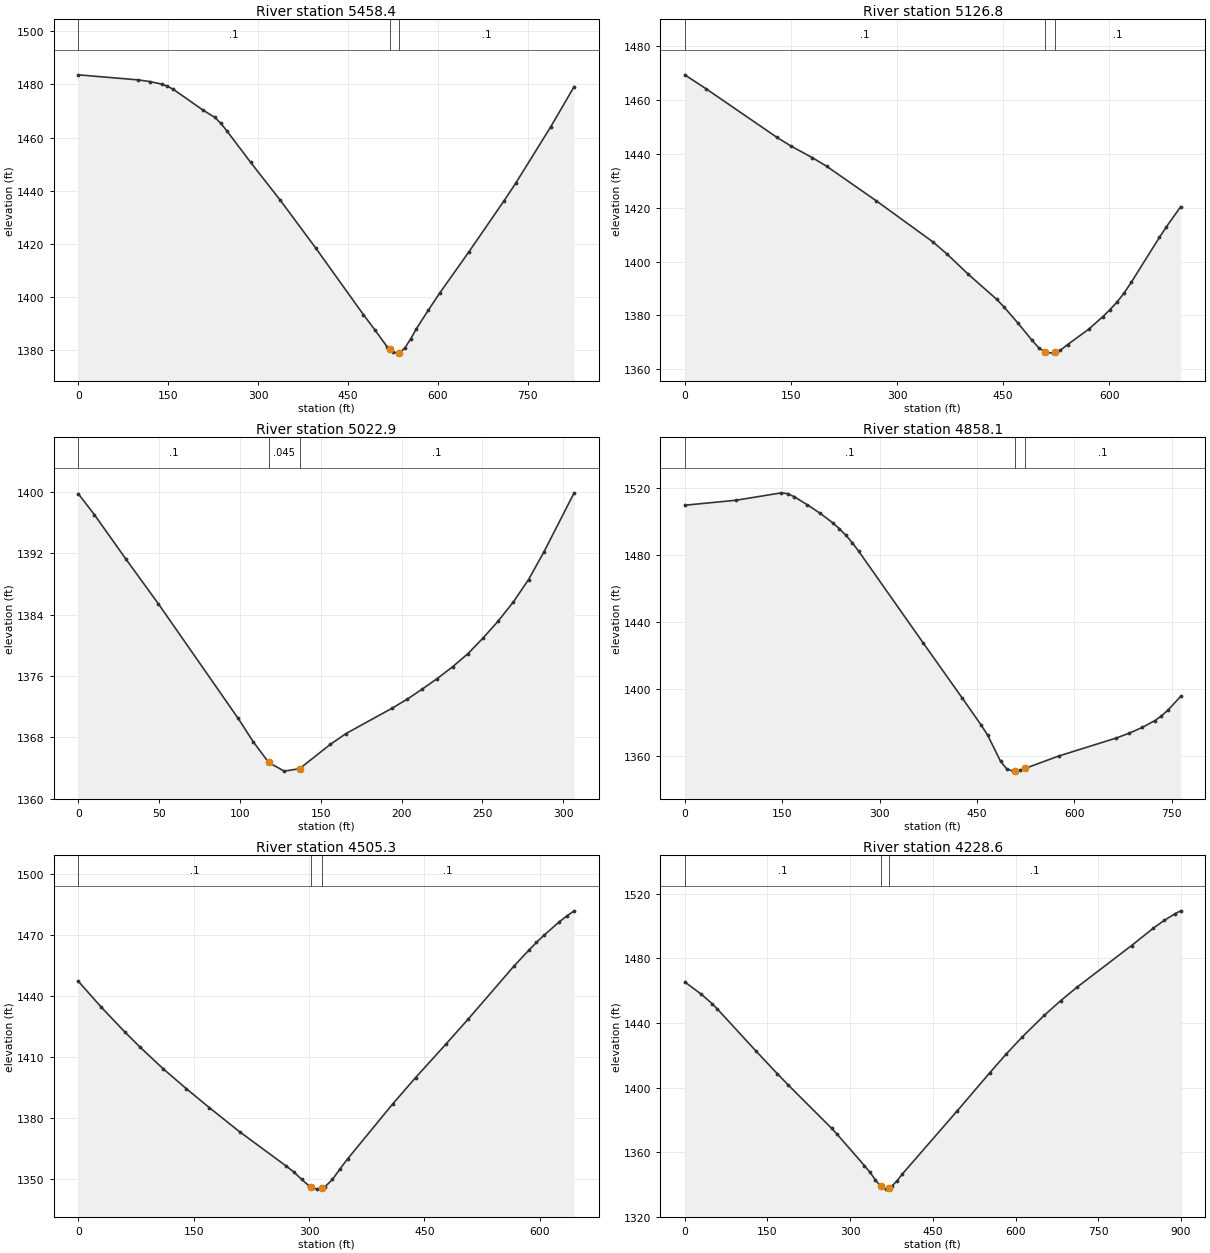
Type RM Length L Ch R = 1 ,5458.4  ,342.7,331.3,321.3
XS GIS Cut Line= 3
     1967022.612      433801.755     1966869.107      434293.848
      1966809.93      434600.146
#Sta/Elev= 30
       0 1483.58    99.1 1481.69     119 1481.07   138.8  1480.1   148.7  1479.3
   158.6 1478.12   208.2  1470.3     228 1467.55   237.9 1465.32   247.8 1462.54
   287.5  1450.7     337 1436.46   396.5 1418.39   475.8 1393.45   495.6 1387.52
   515.5 1381.32   519.5 1380.46   525.2 1379.24   534.5 1379.01     535    1379
   544.7 1380.87   554.5 1384.32   564.2 1388.19   583.7 1395.03   603.2 1401.62
     652 1417.15   710.5 1436.29     730  1442.9   788.4 1464.08   827.4 1479.17
#Mann= 3 , 0 , 0
       0      .1       0   519.5    .045       0   534.5      .1       0
Bank Sta=519.5,534.5
XS Rating Curve= 0 ,0
Exp/Cntr=0.3,0.1

Type RM Length L Ch R = 1 ,5126.8  ,115.6,104,91.7
XS GIS Cut Line= 3
     1966416.881      433839.859      1966555.19      434373.089
     1966663.385      434476.712
#Sta/Elev= 30
       0 1469.41      30 1464.24   130.2 1446.16   150.2 1442.92   180.3 1438.61
   200.3 1435.45   270.4 1422.61   350.6 1407.31   370.6 1402.77   400.6 1395.27
   440.7 1385.98   450.7 1383.22   470.8 1377.14   490.8 1370.68   500.8 1367.76
   508.5 1366.53   510.8 1366.16   520.8 1365.95   523.5 1366.23   530.8    1367
   540.9 1369.13   570.8 1374.84   590.8 1379.53   600.8  1382.1   610.8 1384.91
   620.8  1388.3   630.8 1392.22   670.7 1408.96   680.7 1412.95   700.7 1420.36
#Mann= 3 , 0 , 0
       0      .1       0   508.5    .045       0   523.5      .1       0
Bank Sta=508.5,523.5
XS Rating Curve= 0 ,0
Exp/Cntr=0.3,0.1

Type RM Length L Ch R = 1 ,5022.9  ,182.7,164.6,147
XS GIS Cut Line= 4
     1966384.996      434265.648       1966431.6      434352.723
     1966484.336      434407.912     1966591.034      434485.176
#Sta/Elev= 23
       0 1399.79     9.9 1397.07    29.6 1391.22    49.4 1385.47    98.8 1370.51
   108.3 1367.41   117.8 1364.73   127.4  1363.6   136.9 1363.92     156  1367.1
   165.6  1368.5   193.9 1371.78   203.3 1372.96   212.7 1374.29   222.1 1375.68
   231.6 1377.22     241 1378.91   250.4 1380.96   259.8 1383.18   269.2 1385.68
   278.6  1388.6     288 1392.16   306.8 1399.91
#Mann= 3 , 0 , 0
       0      .1       0   117.8    .045       0   136.9      .1       0
Bank Sta=117.8,136.9
XS Rating Curve= 0 ,0
Exp/Cntr=0.3,0.1

Type RM Length L Ch R = 1 ,4858.1  ,340.8,352.7,364.3
XS GIS Cut Line= 3
     1965817.389      434475.773     1966472.072      434482.723
     1966573.864      434520.742
#Sta/Elev= 30
       0 1509.72    79.4 1512.72   148.8 1517.12   158.7  1516.6   168.6 1514.78
   188.5 1510.02   208.3 1504.96   228.2  1499.1   238.1 1495.66     248 1491.84
   257.9 1487.38   267.8 1482.26     367  1427.6   426.6 1395.01   456.3 1378.58
   466.2 1372.62   486.1 1357.02     496 1352.28   505.9 1351.09   508.6 1351.25
   515.8 1351.68   523.6 1352.66   575.4 1360.06   664.6 1370.88   684.4 1373.74
   704.1 1377.14   723.9 1381.26   733.7 1383.98   743.6  1387.4   763.4 1395.64
#Mann= 3 , 0 , 0
       0      .1       0   508.6    .045       0   523.6      .1       0
Bank Sta=508.6,523.6
XS Rating Curve= 0 ,0
Exp/Cntr=0.3,0.1

Type RM Length L Ch R = 1 ,4505.3  ,272.2,276.7,281.6
XS GIS Cut Line= 3
     1966105.649      434665.672     1966391.349      434831.605
     1966686.243      434939.968
#Sta/Elev= 30
       0 1447.11      30 1434.29    60.1  1422.3    80.1 1414.74   110.1 1404.12
   140.2 1394.32   170.2 1384.97   210.2  1372.9   270.3 1356.18   280.3  1353.2
   290.3 1349.63   300.4  1346.3   302.1 1346.05   310.4 1344.82   317.1 1345.54
   320.4  1345.9   330.4 1349.59   340.2 1354.79     350 1359.67   408.9 1386.83
   438.4 1399.68   477.7  1416.1   507.1  1428.6     566 1454.43   585.7  1462.4
   595.5 1466.19   605.3 1469.72   624.9 1476.24   634.8 1479.18   644.6 1481.77
#Mann= 3 , 0 , 0
       0      .1       0   302.1    .045       0   317.1      .1       0
Bank Sta=302.1,317.1
XS Rating Curve= 0 ,0
Exp/Cntr=0.3,0.1

Type RM Length L Ch R = 1 ,4228.6  ,279.5,297.6,304.7
XS GIS Cut Line= 3
     1965912.118      434776.914     1966213.844      435046.639
     1966548.828       435410.63
#Sta/Elev= 30
       0 1465.36    29.6 1457.85    49.4    1452    59.2 1448.55   128.3  1422.9
   167.8 1408.57   187.6 1401.59   266.5 1374.73   276.4 1371.06   325.7 1351.72
   335.6 1347.68   345.5 1342.96   355.1 1338.87   365.2 1337.11   370.1 1337.93
   375.1 1338.77     385 1342.31   394.8 1346.54   493.8 1385.41   553.1  1409.1
   582.8 1420.66   612.5 1431.46     652 1444.69   681.7 1453.74   711.4  1462.1
   810.3 1487.88   849.9 1498.66   869.7 1503.52   889.5 1507.63   899.4  1509.4
#Mann= 3 , 0 , 0
       0      .1       0   355.1    .045       0   370.1      .1       0
Bank Sta=355.1,370.1
XS Rating Curve= 0 ,0
Exp/Cntr=0.3,0.1

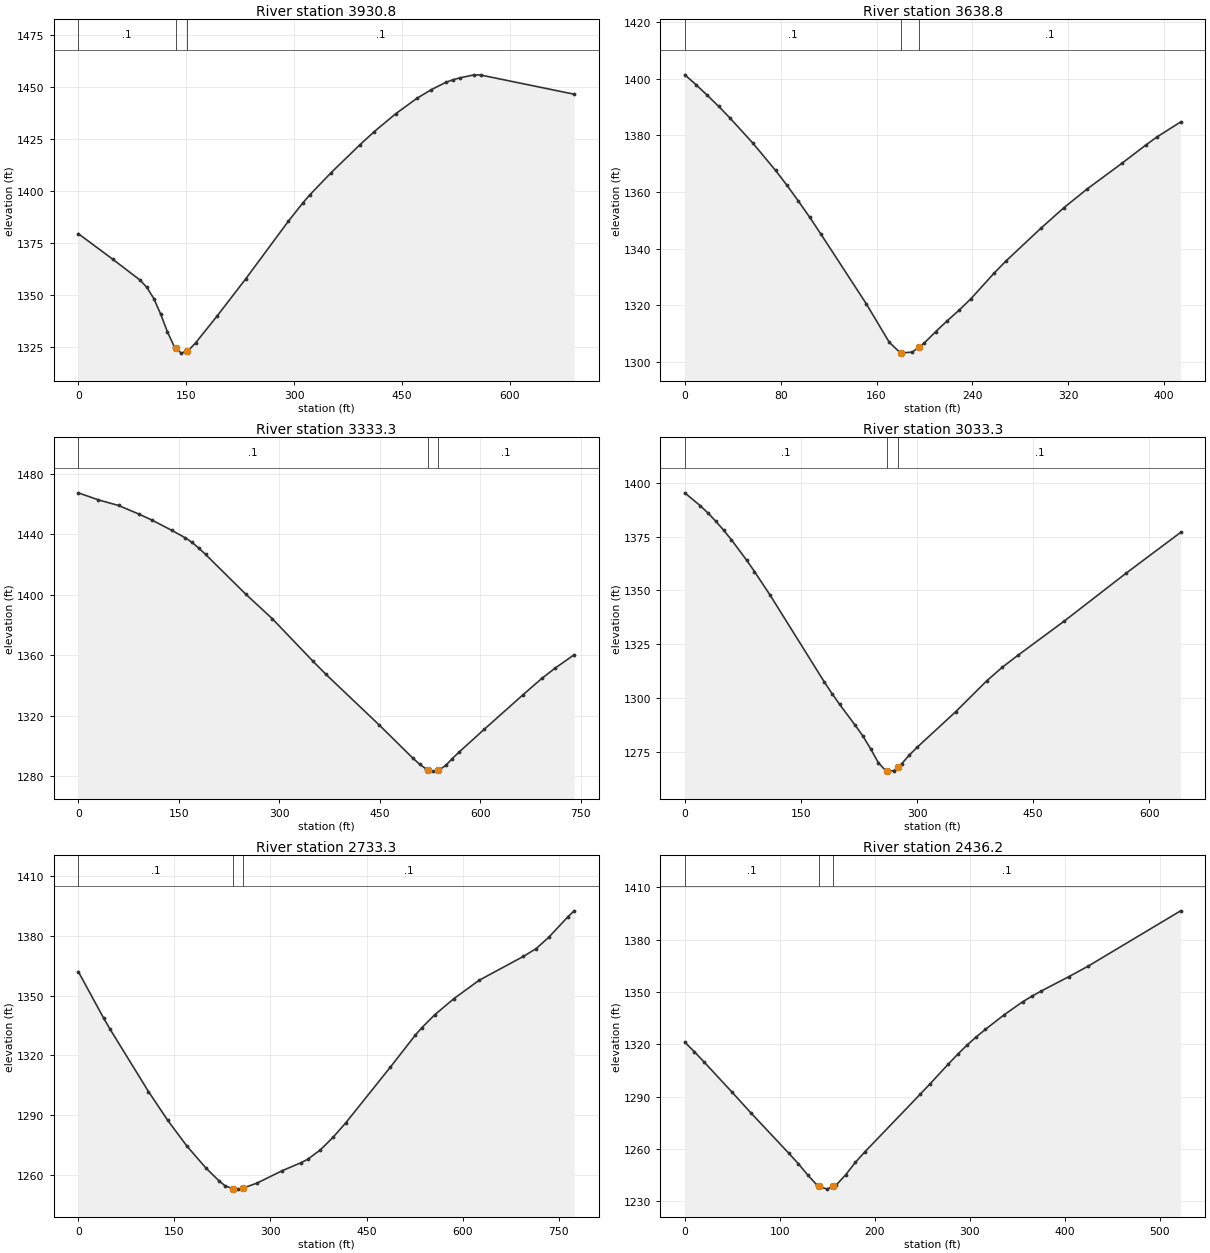
Type RM Length L Ch R = 1 ,3930.8  ,319.1,291.7,275.2
XS GIS Cut Line= 3
     1965938.024      435045.115     1965943.171      435188.027
     1966210.994      435663.966
#Sta/Elev= 30
       0 1379.45    47.7  1367.2    85.8 1357.12    95.3  1353.6   104.9 1348.25
   114.4  1340.8   123.9  1332.2   133.5 1325.02   135.5 1324.39     143 1322.02
   150.5 1322.99   152.9  1323.3   162.9 1326.91   192.6 1339.74   232.4 1357.62
     292 1385.49   311.8 1394.12   321.7 1398.12   351.5 1408.84   391.2 1422.15
   411.1 1428.46   440.9 1437.06   470.7 1444.56   490.5 1448.68   510.4 1452.14
   520.3 1453.41   530.2 1454.34   550.1 1455.82     560 1455.67   689.1  1446.5
#Mann= 3 , 0 , 0
       0      .1       0   135.5    .045       0   150.5      .1       0
Bank Sta=135.5,150.5
XS Rating Curve= 0 ,0
Exp/Cntr=0.3,0.1

Type RM Length L Ch R = 1 ,3638.8  ,292.9,305.5,315.6
XS GIS Cut Line= 3
     1965547.913      435182.263     1965668.299      435288.934
     1965907.546      435371.223
#Sta/Elev= 30
       0 1401.44     9.5 1397.91    18.9 1394.15    28.4 1390.25    37.8 1386.12
    56.8 1377.29    75.7 1367.67    85.2 1362.41    94.6 1356.91   104.1 1351.16
   113.5 1345.17   151.4 1320.52   170.6 1306.91   180.1 1303.03     190 1303.42
   195.1 1305.07   199.8  1306.6   209.5 1310.67   219.2 1314.55     229 1318.25
   238.7 1322.23   258.2 1331.34   267.9 1335.55   297.1 1347.15   316.5  1354.5
     336 1361.14   365.2 1370.28   384.7  1376.6   394.4 1379.57   413.8 1384.77
#Mann= 3 , 0 , 0
       0      .1       0   180.1    .045       0   195.1      .1       0
Bank Sta=180.1,195.1
XS Rating Curve= 0 ,0
Exp/Cntr=0.3,0.1

Type RM Length L Ch R = 1 ,3333.3  ,323.6,299.9,277.7
XS GIS Cut Line= 3
     1965167.743      435118.129      1965502.58       435528.47
      1965653.06      435675.997
#Sta/Elev= 30
       0 1467.33      30 1462.67      60 1458.96    89.9 1453.38   109.9 1449.32
   139.9 1442.42   159.9 1437.52   169.9  1434.5   179.9 1430.73   189.9 1426.63
   249.8 1400.38   289.8 1383.98   349.8 1356.18   369.7 1347.26   449.7 1313.56
   499.6 1291.77   509.6 1287.81   519.6 1284.55   522.1 1284.21   529.6  1283.2
   537.1 1283.86   539.2 1284.04   548.8 1287.06   558.4 1291.48   567.9 1295.54
   606.2  1310.9   663.7 1333.59   692.5 1344.69   711.6  1351.2   740.4 1360.21
#Mann= 3 , 0 , 0
       0      .1       0   522.1    .045       0   537.1      .1       0
Bank Sta=522.1,537.1
XS Rating Curve= 0 ,0
Exp/Cntr=0.3,0.1

Type RM Length L Ch R = 1 ,3033.3  ,298.9,300,300.9
XS GIS Cut Line= 3
     1965109.039       435779.62     1965359.162      435780.633
     1965741.445      435701.902
#Sta/Elev= 30
       0 1395.37      20 1389.37      30 1385.96      40 1382.18      50 1378.07
      60 1373.64      80    1364      90 1358.78   110.1 1347.86   180.1  1307.5
   190.1 1302.07   200.1 1296.97   220.1 1287.31   230.1 1282.27   240.1 1276.28
   250.1 1269.86   260.1 1265.99   260.7    1266   270.1 1266.22   275.7 1268.01
   280.2 1269.44   290.2 1273.54   300.2 1277.11   350.2 1293.71   390.2 1308.05
   410.2 1314.32   430.3 1319.85   490.3  1335.8   570.4 1358.12   640.4 1376.97
#Mann= 3 , 0 , 0
       0      .1       0   260.7    .045       0   275.7      .1       0
Bank Sta=260.7,275.7
XS Rating Curve= 0 ,0
Exp/Cntr=0.3,0.1

Type RM Length L Ch R = 1 ,2733.3  ,274.7,296.9,320.3
XS GIS Cut Line= 3
     1965311.714      436037.153     1965558.706      436006.167
     1966076.607      435918.227
#Sta/Elev= 30
       0 1362.04    39.8 1338.51    49.8 1332.98   109.5 1301.76   139.4 1287.36
   169.3 1274.42   199.1 1263.34   219.1    1257     229 1254.38   241.4 1252.85
   248.9 1252.67   256.4 1253.11   278.7 1255.66   318.3 1261.93     348 1266.01
     358 1267.66   377.8 1272.37   397.6  1278.7   417.4 1285.94   486.8 1313.86
   526.4 1330.21   536.4 1333.86   556.2 1340.27   585.9 1348.33   625.6 1357.67
     695 1369.72   714.8 1373.62   734.6 1379.34   764.3 1389.59   774.2 1392.63
#Mann= 3 , 0 , 0
       0      .1       0   241.4    .045       0   256.4      .1       0
Bank Sta=241.4,256.4
XS Rating Curve= 0 ,0
Exp/Cntr=0.3,0.1

Type RM Length L Ch R = 1 ,2436.2  ,337.9,331.2,324.5
XS GIS Cut Line= 3
     1965387.907      436166.682     1965503.721       436303.83
     1965802.399      436471.456
#Sta/Elev= 30
       0 1321.18      10 1315.72      20    1310    49.9 1292.43    69.8 1280.53
   109.7 1257.41   119.7 1251.43   129.6 1244.94   139.6 1239.03   141.4 1238.66
   149.6 1236.95   156.4 1238.62   159.6  1239.4   169.5 1245.25   179.5 1252.26
   189.3 1258.15     248 1291.44   257.8 1297.05   277.4 1308.61   287.2 1314.17
   296.9 1319.39   306.7 1324.12   316.5 1328.53   336.1  1336.8   355.6  1344.3
   365.4 1347.51   375.2 1350.46   404.6 1358.81   424.2  1364.6     522 1396.45
#Mann= 3 , 0 , 0
       0      .1       0   141.4    .045       0   156.4      .1       0
Bank Sta=141.4,156.4
XS Rating Curve= 0 ,0
Exp/Cntr=0.3,0.1

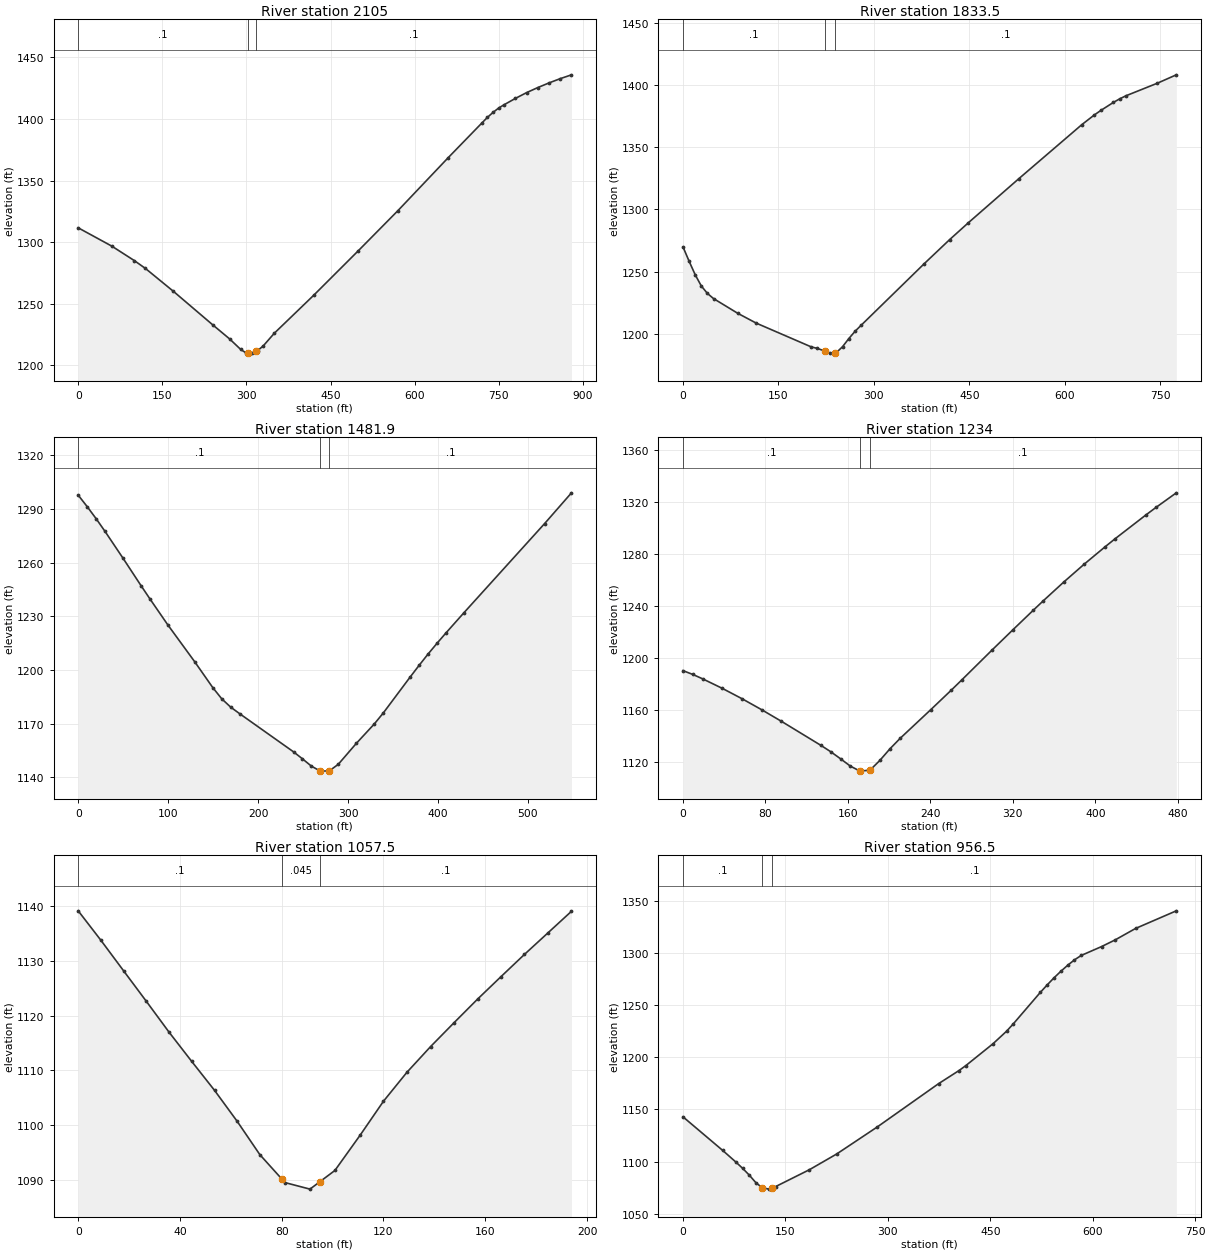
Type RM Length L Ch R = 1 ,2105    ,273.1,271.3,269.5
XS GIS Cut Line= 2
     1964974.939      436328.212     1965714.484      436804.179
#Sta/Elev= 30
       0 1311.61      60  1296.7    99.9 1285.02   119.9 1278.58   169.9 1259.94
   239.9 1232.75   269.8  1221.4   289.8 1212.75   299.8 1209.79   301.9  1209.8
   309.8 1209.82   316.9 1211.21   319.8 1211.78   329.8 1215.61   349.8 1226.03
   419.8 1256.76   499.7 1293.11   569.7 1325.41   659.6 1368.56   719.6 1396.71
   729.6 1401.34   739.6 1405.38   749.6 1408.92   759.5 1411.65   779.5 1416.75
   799.5 1421.46   819.5 1425.58   839.5 1429.35   859.5 1432.82   879.5 1435.91
#Mann= 3 , 0 , 0
       0      .1       0   301.9    .045       0   316.9      .1       0
Bank Sta=301.9,316.9
XS Rating Curve= 0 ,0
Exp/Cntr=0.3,0.1

Type RM Length L Ch R = 1 ,1833.5  ,360.8,351.2,341.6
XS GIS Cut Line= 3
     1965032.846      436552.221     1965116.659      436735.085
     1965621.884      437007.167
#Sta/Elev= 30
       0 1269.76     9.6 1258.24    19.2 1247.34    28.7 1238.42    38.3  1232.4
    47.9 1228.27    86.2 1216.35     115 1208.53   201.2 1189.47     211 1188.19
   223.5 1185.93   230.8  1184.4   238.5 1184.66   240.7 1184.73   250.6 1189.54
   260.5  1196.1   270.4 1202.02   280.3 1207.02   379.2 1256.42   418.8 1275.61
   448.5  1289.3   527.6 1324.64   626.6 1368.09   646.4 1375.93   656.3 1379.45
     676 1385.89   685.9 1388.77   695.8 1391.26   745.3  1401.4     775 1408.12
#Mann= 3 , 0 , 0
       0      .1       0   223.5    .045       0   238.5      .1       0
Bank Sta=223.5,238.5
XS Rating Curve= 0 ,0
Exp/Cntr=0.3,0.1

Type RM Length L Ch R = 1 ,1481.9  ,239.8,247.9,253.8
XS GIS Cut Line= 2
     1964703.691      437029.191     1965250.759      437068.812
#Sta/Elev= 30
       0  1297.7      10 1291.27      20 1284.51    29.9  1277.4    49.9 1262.41
    69.8 1247.19    79.8  1239.7    99.7 1225.18   129.6 1204.58   149.6  1190.2
   159.6 1183.92   169.5 1179.28   179.5 1175.61   239.4 1154.29   249.3  1150.4
   259.3 1146.29   269.3 1143.51   279.2 1143.64   289.2 1147.33   309.2 1158.99
   329.1 1169.79   339.1 1175.92     369 1196.01     379 1202.57   388.9 1208.86
   398.9 1214.89   408.9 1220.71   428.8 1231.95   518.6 1281.82   548.5    1299
#Mann= 3 , 0 , 0
       0      .1       0   269.3    .045       0   279.2      .1       0
Bank Sta=269.3,279.2
XS Rating Curve= 0 ,0
Exp/Cntr=0.3,0.1

Type RM Length L Ch R = 1 ,1234    ,164.3,176.5,190.7
XS GIS Cut Line= 3
     1964801.368       437219.35     1964974.939      437298.916
     1965255.331      437362.919
#Sta/Elev= 30
       0 1190.35     9.6  1187.4    19.1 1184.04    38.2 1176.69    57.3 1168.73
    76.4 1160.25    95.5 1151.35   133.7 1132.89   143.2 1128.02   152.8 1122.55
   162.3  1116.9   171.7 1113.04   181.4  1113.8   190.9 1121.25   200.9 1130.36
   210.8  1138.4   240.5 1160.46   260.4 1175.48   270.3 1183.13     300  1206.4
   319.9 1221.73   339.7  1236.8   349.6 1244.21   369.4 1258.59   389.3 1272.39
   409.1 1285.45     419 1291.77   448.8 1310.04   458.7  1315.9   478.5 1327.19
#Mann= 3 , 0 , 0
       0      .1       0   171.7    .045       0   181.4      .1       0
Bank Sta=171.7,181.4
XS Rating Curve= 0 ,0
Exp/Cntr=0.3,0.1

Type RM Length L Ch R = 1 ,1057.5  ,100.1,100.9,101.4
XS GIS Cut Line= 4
     1964811.885      437361.395     1964851.506      437420.826
     1964874.364      437452.827     1964947.509      437492.447
#Sta/Elev= 24
       0 1139.07     8.9 1133.72    17.9 1128.11    26.8 1122.58    35.7 1116.98
    44.6 1111.66    53.6 1106.37    62.5 1100.73    71.4 1094.67      80 1090.25
    81.3 1089.58    91.1 1088.39      95 1089.74   100.9 1091.79   110.8  1098.2
     120  1104.4   129.2 1109.66   138.5 1114.34   147.7 1118.68     157    1123
   166.2 1127.09   175.4 1131.13   184.7 1135.08   193.9 1138.99
#Mann= 3 , 0 , 0
       0      .1       0      80    .045       0      95      .1       0
Bank Sta=80,95
XS Rating Curve= 0 ,0
Exp/Cntr=0.3,0.1

Type RM Length L Ch R = 1 ,956.5   ,214.3,187.2,160.6
XS GIS Cut Line= 3
     1964708.262      437384.253     1964787.503      437506.162
     1965311.328      437748.378
#Sta/Elev= 30
       0 1142.82    58.2 1110.62    77.6 1099.43    87.2 1093.58    96.9 1087.12
   106.6 1079.87   115.9 1074.93     126  1073.6   130.9 1074.84   135.7 1076.06
   185.2 1092.23     225 1107.23   284.7 1133.23   374.3 1174.61   404.1 1187.12
   414.1 1191.86   453.9 1212.77   473.8  1224.8   483.7 1231.85   523.5 1262.16
   533.5 1269.27   543.4    1276   553.4 1282.24   563.3 1287.95   573.3 1293.17
   583.2  1297.4   613.1 1305.93     633 1312.32   662.8 1323.26   722.5 1340.15
#Mann= 3 , 0 , 0
       0      .1       0   115.9    .045       0   130.9      .1       0
Bank Sta=115.9,130.9
XS Rating Curve= 0 ,0
Exp/Cntr=0.3,0.1

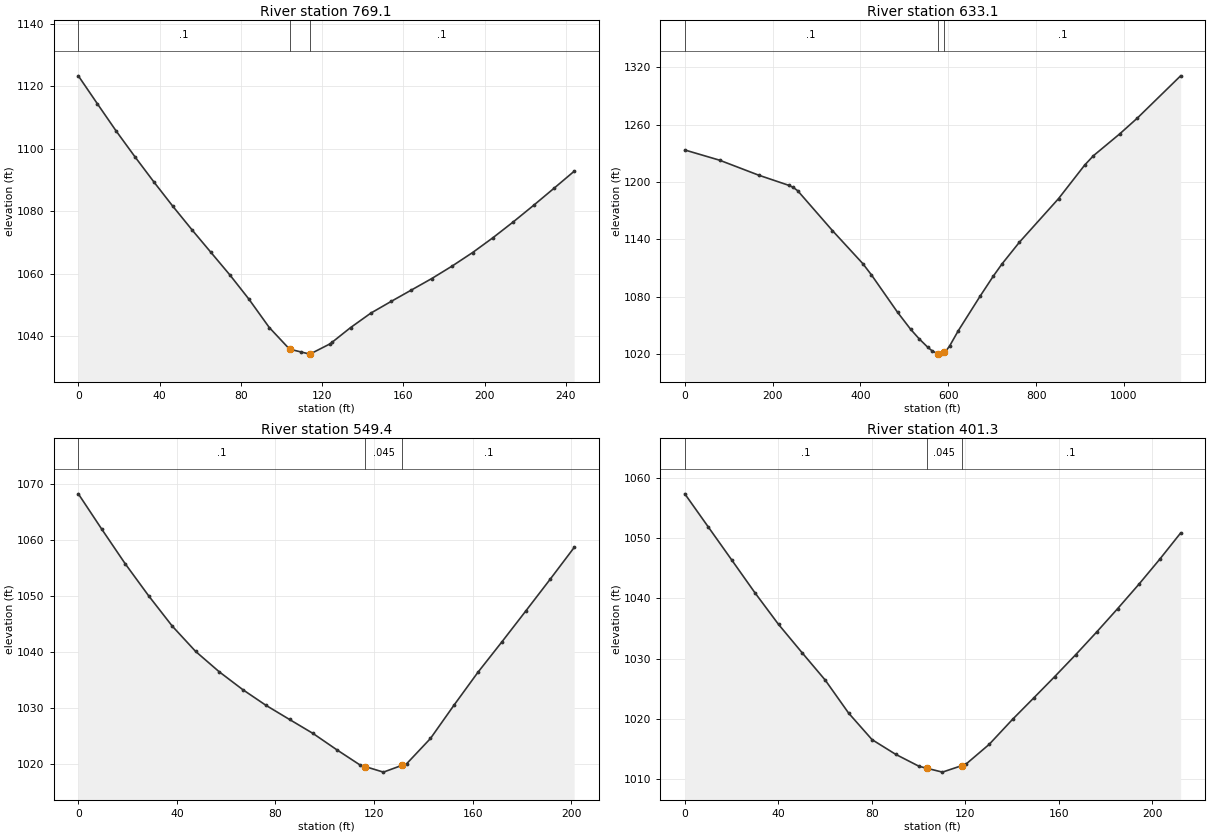
Type RM Length L Ch R = 1 ,769.1   ,129,136,142.8
XS GIS Cut Line= 3
     1964598.544      437629.595     1964679.309      437652.453
     1964836.267      437620.452
#Sta/Elev= 28
       0 1123.36     9.3 1114.48    18.6  1105.7      28 1097.31    37.3 1089.27
    46.6  1081.5      56 1073.98    65.3 1066.77    74.6 1059.56    83.9 1051.87
      94 1042.71     104 1035.77   109.8 1034.85     114 1034.18     124  1037.5
   124.8 1037.91     134 1042.67     144 1047.32     154 1051.07     164 1054.73
     174  1058.4     184 1062.39   194.1 1066.73   204.1 1071.47   214.1 1076.54
   224.1 1081.84   234.1 1087.28   244.1 1092.78
#Mann= 3 , 0 , 0
       0      .1       0     104    .045       0     114      .1       0
Bank Sta=104,114
XS Rating Curve= 0 ,0
Exp/Cntr=0.3,0.1

Type RM Length L Ch R = 1 ,633.1   ,79.6,83.5,87.8
XS GIS Cut Line= 3
      1964171.66      437713.625     1964751.543      437775.154
     1965294.941      437825.783
#Sta/Elev= 30
       0 1233.56    79.1 1222.89     168 1207.26   237.2 1196.54   247.1 1194.36
     257 1190.98     336 1149.37   405.2 1114.84     425 1102.98   484.3 1064.02
     514 1046.27   533.7 1036.15   553.5 1027.26   563.4 1023.52   575.6 1020.73
   583.1  1020.2   590.6 1021.97   593.1 1022.56     603 1028.75   622.8 1044.76
   672.4 1080.78   702.2 1101.58   722.1  1114.4   761.8 1137.14     851 1182.75
   910.6 1217.85   930.4 1227.57     990 1250.28  1029.7  1266.6  1128.9 1311.05
#Mann= 3 , 0 , 0
       0      .1       0   575.6    .045       0   590.6      .1       0
Bank Sta=575.6,590.6
XS Rating Curve= 0 ,0
Exp/Cntr=0.3,0.1

Type RM Length L Ch R = 1 ,549.4   ,142.2,148.1,154.2
XS GIS Cut Line= 3
     1964632.069      437823.127      1964778.36      437865.795
     1964827.124      437865.795
#Sta/Elev= 24
       0 1068.22     9.5 1061.91      19 1055.74    28.6 1049.96    38.1 1044.59
    47.6 1040.06    57.2 1036.41    66.7 1033.24    76.2 1030.41    85.7  1027.9
    95.2 1025.41   104.8 1022.51   114.3 1019.77   116.5 1019.47   123.8 1018.49
   131.5 1019.73   133.3 1020.02   142.9 1024.51   152.4 1030.43   162.1  1036.3
   171.9 1041.78   181.6  1047.3   191.4 1052.92   201.2 1058.63
#Mann= 3 , 0 , 0
       0      .1       0   116.5    .045       0   131.5      .1       0
Bank Sta=116.5,131.5
XS Rating Curve= 0 ,0
Exp/Cntr=0.3,0.1

Type RM Length L Ch R = 1 ,401.3   ,409.5,401.3,393
XS GIS Cut Line= 3
     1964586.325      437929.012     1964705.696      438002.597
     1964774.375      438023.855
#Sta/Elev= 25
       0 1057.37      10 1051.89      20 1046.42      30 1040.93    40.1 1035.67
    50.1    1031    60.1  1026.4    70.1 1020.92    80.1 1016.52    90.2 1014.08
   100.2 1012.09   103.5 1011.77   110.2 1011.12   118.5  1012.2   120.2 1012.42
   130.2 1015.73   140.2 1019.89   149.2 1023.42   158.2 1026.98   167.2 1030.63
   176.2 1034.41   185.2 1038.31   194.2 1042.32   203.1 1046.47   212.1 1050.86
#Mann= 3 , 0 , 0
       0      .1       0   103.5    .045       0   118.5      .1       0
Bank Sta=103.5,118.5
XS Rating Curve= 0 ,0
Exp/Cntr=0.3,0.1

Chan Stop Cuts=-1
Use User Specified Reach Order=0
Composite Channel Slope=5